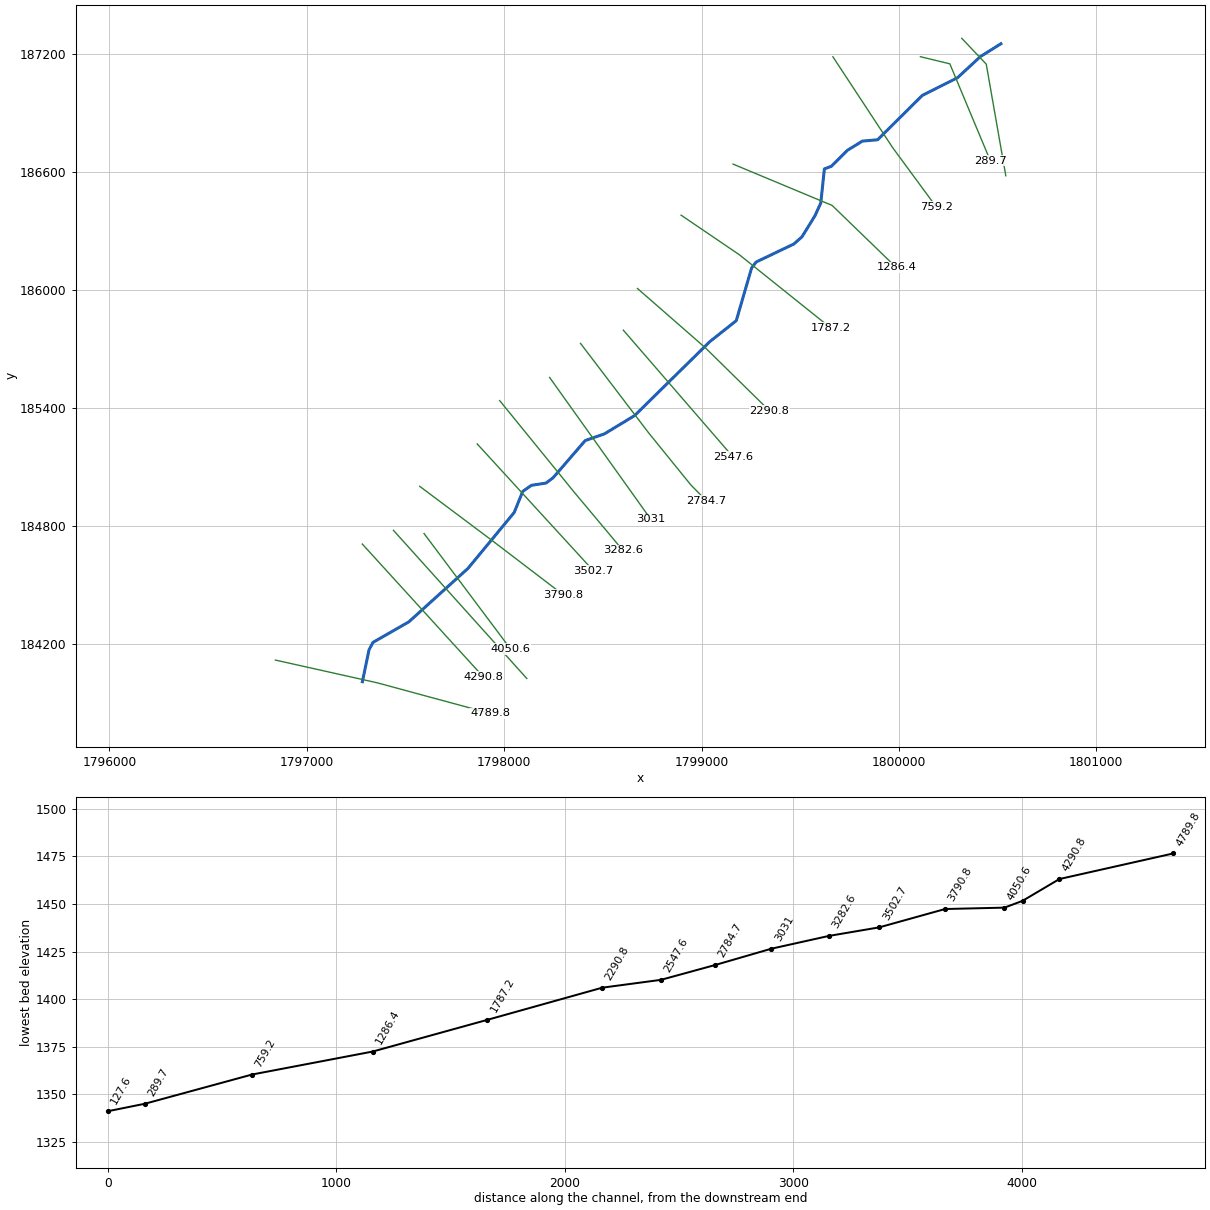
--- BaileyBr.prj (project) ---

Proj Title=BaileyBr
Current Plan=p01
Geom File=g01
Flow File=f01
Plan File=p01
DSS Export Rating Curves=0
DSS Export Rating Curve Sorted=0
DSS Export Volume Flow Curves=0
DXF OffsetX=0
DXF OffsetY=0
DXF ScaleX=0
DXF ScaleY=0

--- BaileyBr.p01 (plan) ---

Plan Title=Floodplain
Program Version=4.00
Geom File=g01
Flow File=f01
K Sum by GR=0
Std Step Tol=0.01
Critical Tol=0.01
Num of Std Step Trials=20
Max Error Tol=0.3
Flow Tol Ratio=0.001
Split Flow NTrial=30
Split Flow Tol=0.02
Split Flow Ratio=0.02
Log Output Level=0
Friction Slope Method=1
Unsteady Friction Slope Method=2
Unsteady Bridges Friction Slope Method=1
Global Log Level=0
CheckData=False
Run HTab=0
Run UNet=0
Run PostProcess=0
UNET Theta=0
UNET Theta Warmup=0
UNET ZTol=0
UNET ZSATol=0
UNET MxIter=0
UNET MaxInSteps=0
UNET DtIC=0
UNET DtMin=0
UNET MaxCRTS=0
UNET WFStab=0
UNET SFStab=0
UNET WFX=0
UNET SFX=0
UNET DSS MLevel=0
UNET DZMax Abort=0
UNET Convert EG Bridges=0
UNET Use Existing IB Tables=0
UNET Froude Limit=0
UNET Froude Power=0
Write IC File=0
Echo Input=False
Echo Output=False
Write Detailed=0

--- BaileyBr.f01 (steady flow) ---

Flow Title=NFF Regression Equation
Program Version=4.00
Number of Profiles=1
Profile Names=P100yr
River Rch & RM=BaileyBr,Main      ,4789.8
262.7910
River Rch & RM=BaileyBr,Main      ,4789.8
262.7910
River Rch & RM=BaileyBr,Main      ,4290.8
381.3417
River Rch & RM=BaileyBr,Main      ,3282.6
422.2860
River Rch & RM=BaileyBr,Main      ,2290.8
447.2147
River Rch & RM=BaileyBr,Main      ,289.7
476.5351
Boundary for River Rch & Prof#=BaileyBr,Main      ,1
Up Type=0
Dn Type=3
Dn Slope=0.025962

--- BaileyBr.g01 (geometry) ---

Geom Title=LiDAR based DEM
Program Version=4.00

River Reach=BaileyBr     ,Main
Reach XY= 30
     1797281.997      184010.761     1797315.615      184172.801
     1797335.786      184210.454     1797517.325      184314.671
     1797817.201      184586.307     1798051.184      184870.045
     1798094.215      184976.951     1798138.592      185007.880
     1798212.552      185019.310     1798248.188      185046.205
     1798410.900      185235.140     1798507.721      185268.759
     1798661.180      185361.836     1799042.252      185737.398
     1799176.053      185843.632     1799254.048      186111.906
     1799276.908      186141.490     1799467.860      186232.932
     1799508.874      186269.240     1799574.766      186376.146
     1799604.351      186441.365     1799622.504      186614.164
     1799658.140      186627.611     1799738.824      186708.295
     1799814.801      186755.360     1799892.123      186762.084
     1800118.711      186987.327     1800297.560      187077.424
     1800412.843      187184.400     1800516.929      187249.521

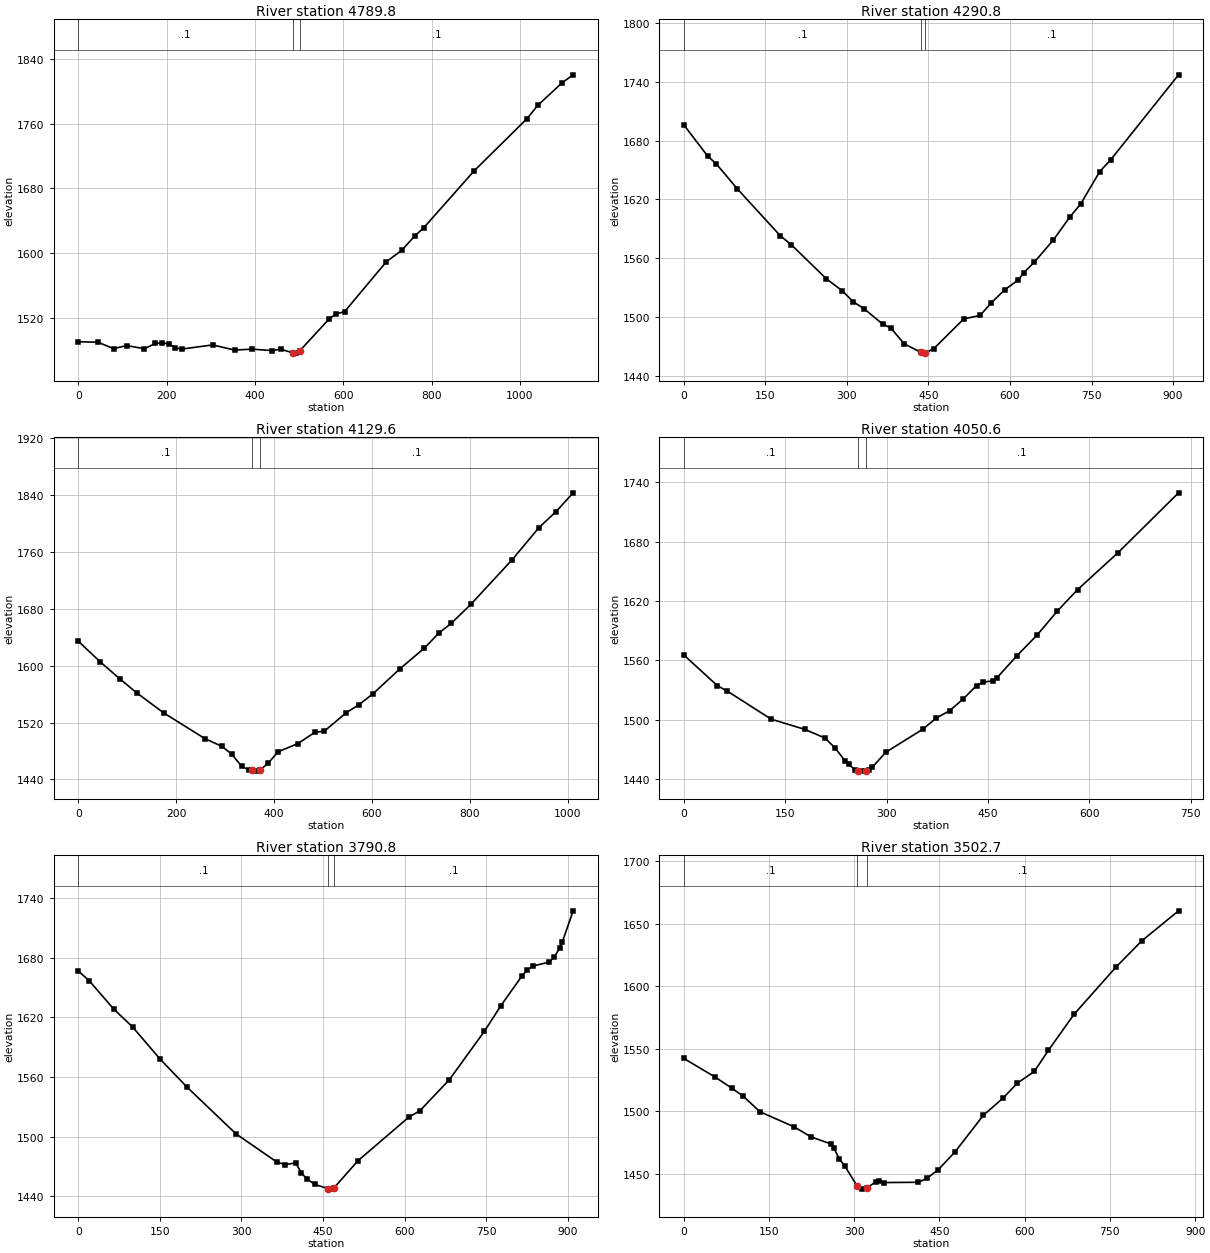
Type RM Length L Ch R = 1 ,4789.8,513.3,499,484.7
XS GIS Cut Line= 3
     1796841.354      184120.683     1797357.158      184005.239
     1797928.645      183850.043
#Sta/Elev= 30
       0 1490.71    44.9 1489.96    79.8 1482.15   109.7 1485.86   149.6 1482.06
   174.5 1488.51   189.5 1489.24   204.4 1488.17   219.4 1483.46   234.4 1481.59
   304.2 1486.71   354.0 1480.38   393.9 1481.49   438.8 1479.72   458.8 1481.42
   486.2 1476.81   493.7 1476.58   501.2 1479.18   568.4 1518.98   583.3 1524.89
   603.2 1527.86   697.8 1589.56   732.6 1603.58   762.4 1621.57   782.4 1631.46
   896.8 1701.93  1016.2 1766.23  1041.1 1782.98  1095.9 1810.67  1120.8 1820.45
#Mann= 3 , 0 , 0
       0     0.1       0   486.2   0.045       0   501.2     0.1       0
Bank Sta=   486.2,   501.2
Exp/Cntr=0.3,0.1

Type RM Length L Ch R = 1 ,4290.8,161.3,161.2,161
XS GIS Cut Line= 3
     1797281.633      184709.635     1797587.699      184372.962
     1797893.765      184036.289
#Sta/Elev= 30
       0 1696.13    44.5 1663.81    59.4 1656.54    98.9 1630.50   178.0 1582.63
   197.8 1573.74   262.1 1539.04   291.8 1526.60   311.6 1515.51   331.4 1508.52
   366.0 1492.66   380.8 1488.77   405.5 1472.61   436.1 1463.90   440.2 1463.10
   444.2 1463.17   460.0 1467.71   515.0 1498.00   545.0 1501.50   565.0 1514.07
   590.0 1527.52   615.0 1537.72   625.0 1544.93   645.0 1556.01   680.0 1578.72
   710.0 1601.88   730.0 1615.23   765.0 1648.31   785.0 1660.23   910.0 1747.02
#Mann= 3 , 0 , 0
       0     0.1       0   436.1   0.045       0   444.2     0.1       0
Bank Sta=   436.1,   444.2
Exp/Cntr=0.3,0.1

Type RM Length L Ch R = 1 ,4129.6,81.1,79.1,77
XS GIS Cut Line= 2
     1797439.320      184779.395     1798114.881      184027.150
#Sta/Elev= 30
       0 1634.30    44.8 1605.25    84.7 1581.45   119.5 1561.64   174.3 1533.58
   259.0 1497.19   293.9 1486.32   313.8 1475.26   333.7 1458.46   348.6 1453.33
   355.7 1452.72   363.6 1451.64   371.4  1453.1   388.5 1463.16   408.4 1478.96
   448.3 1490.20   483.1 1506.08   503.0 1508.03   547.9 1533.98   572.8 1544.64
   602.7 1560.70   657.4 1595.66   707.2 1624.58   737.1 1646.02   762.0 1659.39
   801.9 1685.98   886.6 1748.90   941.3 1794.08   976.2 1816.48  1011.1 1842.87
#Mann= 3 , 0 , 0
       0     0.1       0   355.7   0.045       0   371.4     0.1       0
Bank Sta=   355.7,   371.4
Exp/Cntr=0.3,0.1

Type RM Length L Ch R = 1 ,4050.6,253.3,259.8,266
XS GIS Cut Line= 2
     1797594.517      184762.962     1798032.718      184176.868
#Sta/Elev= 30
       0 1565.49    49.8 1534.39    64.7 1528.79   129.4 1500.54   179.2 1490.21
   209.1 1481.46   224.0 1471.32   239.0 1458.13   243.9 1454.80   253.9 1449.38
   258.1 1448.34   263.8 1448.07   269.4 1448.46   273.8 1449.04   278.8 1451.82
   298.7 1467.02   353.4 1490.34   373.4 1501.60   393.3 1509.16   413.2 1520.82
   433.1 1534.55   443.1 1537.95   458.0 1539.40   463.0 1542.20   492.8 1564.65
   522.7 1585.58   552.6 1609.81   582.4 1631.36   642.2 1668.69   731.8 1729.19
#Mann= 3 , 0 , 0
       0     0.1       0   258.1   0.045       0   269.4     0.1       0
Bank Sta=   258.1,   269.4
Exp/Cntr=0.3,0.1

Type RM Length L Ch R = 1 ,3790.8,293.2,288.1,283.2
XS GIS Cut Line= 3
     1797572.358      185002.712     1797936.356      184729.715
     1798297.826      184453.335
#Sta/Elev= 30
       0 1666.50    20.0 1656.70    65.0 1628.34   100.0 1610.16   150.0 1578.21
   200.0 1549.78   290.0 1502.88   365.0 1474.58   380.0 1471.97   400.0 1473.68
   410.0 1463.75   420.0 1457.81   435.0 1452.07   459.9 1447.68   464.9 1447.34
   469.8 1448.30   514.4 1475.90   608.3 1519.86   628.1 1525.99   682.5 1557.37
   746.8 1605.90   776.5 1631.09   816.0 1661.60   825.9 1667.61   835.8 1671.40
   865.5 1675.36   875.4 1680.49   885.3 1689.58   890.2 1695.78   910.0 1726.90
#Mann= 3 , 0 , 0
       0     0.1       0   459.9   0.045       0   469.8     0.1       0
Bank Sta=   459.9,   469.8
Exp/Cntr=0.3,0.1

Type RM Length L Ch R = 1 ,3502.7,221,220.1,219.2
XS GIS Cut Line= 2
     1797863.726      185217.900     1798451.241      184575.205
#Sta/Elev= 30
       0 1542.31    54.7 1527.53    84.6 1518.49   104.5 1512.12   134.4 1499.53
   194.1 1487.60   223.9 1479.52   258.7 1473.94   263.7 1471.00   273.7 1462.02
   283.6 1456.14   305.2 1440.18   313.5 1437.70   321.7 1438.42   338.4 1443.70
   343.3 1444.06   353.3 1442.96   413.0 1443.18   427.9 1446.34   447.8 1453.11
   477.7 1467.62   527.4 1496.84   562.3 1510.65   587.1 1522.52   617.0 1531.85
   641.9 1548.83   686.7 1577.48   761.3 1615.67   806.1 1636.34   870.8 1660.36
#Mann= 3 , 0 , 0
       0     0.1       0   305.2   0.045       0   321.7     0.1       0
Bank Sta=   305.2,   321.7
Exp/Cntr=0.3,0.1

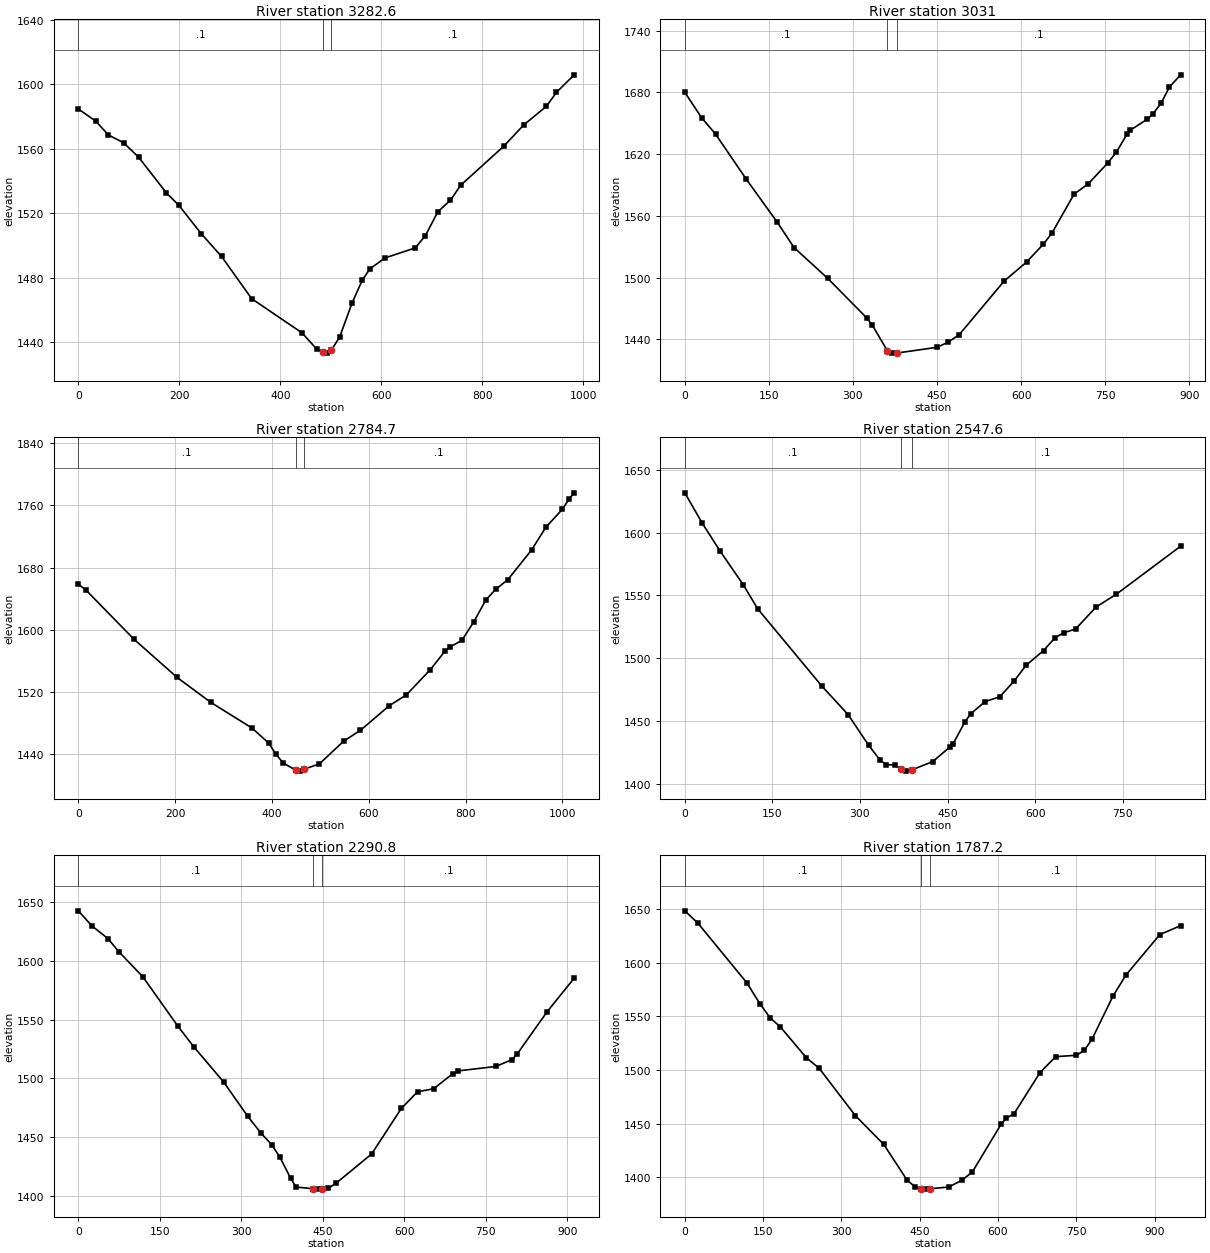
Type RM Length L Ch R = 1 ,3282.6,252.9,251.6,250.2
XS GIS Cut Line= 3
     1797977.511      185437.982     1798353.862      184974.455
     1798600.554      184679.075
#Sta/Elev= 30
       0 1584.63    34.8 1576.96    59.7 1568.45    89.6 1563.66   119.4 1554.68
   174.2 1532.64   199.0 1524.87   243.8 1507.12   283.6 1493.16   343.3 1466.95
   442.8 1445.80   472.8 1435.46   484.3 1433.97   492.6 1433.20   500.8 1434.91
   517.5 1443.17   542.3 1464.49   562.2 1478.36   577.2 1485.38   607.1 1492.22
   667.0 1498.42   687.0 1505.88   712.0 1520.91   737.0 1528.01   757.0 1537.25
   842.0 1561.38   882.0 1574.68   926.9 1586.26   946.9 1594.92   981.9 1605.78
#Mann= 3 , 0 , 0
       0     0.1       0   484.3   0.045       0   500.8     0.1       0
Bank Sta=   484.3,   500.8
Exp/Cntr=0.3,0.1

Type RM Length L Ch R = 1 ,3031,245.7,246.3,247
XS GIS Cut Line= 2
     1798230.517      185555.478     1798743.375      184834.880
#Sta/Elev= 30
       0 1680.12    30.0 1655.48    55.0 1639.41   109.9 1595.48   164.9 1553.82
   194.9 1529.14   254.8 1499.28   324.8 1460.57   334.8 1453.38   361.3 1428.90
   369.8 1426.48   378.2 1426.56   449.7 1432.11   469.7 1437.07   489.7 1444.51
   569.7 1496.57   609.6 1515.03   639.6 1532.44   654.6 1542.95   694.6 1581.27
   719.6 1591.04   754.6 1611.50   769.5 1621.63   789.5 1640.04   794.5 1643.24
   824.5 1653.84   834.5 1658.78   849.5 1669.39   864.5 1685.21   884.5 1697.17
#Mann= 3 , 0 , 0
       0     0.1       0   361.3   0.045       0   378.2     0.1       0
Bank Sta=   361.3,   378.2
Exp/Cntr=0.3,0.1

Type RM Length L Ch R = 1 ,2784.7,235.7,237.1,238.6
XS GIS Cut Line= 4
     1798387.020      185728.541     1798730.391      185276.327
     1798946.890      185008.737     1799025.771      184929.012
#Sta/Elev= 30
       0 1658.55    14.9 1651.54   114.6 1587.90   204.2 1538.45   273.9 1506.30
   358.6 1473.42   393.5 1453.84   408.4 1439.38   423.4 1428.38   449.6 1418.85
   458.2 1417.90   466.7 1420.44   498.1 1427.31   547.9 1456.41   582.8 1470.48
   642.6 1502.30   677.6 1516.05   727.4 1548.74   757.4 1572.48   767.3 1577.54
   792.3 1586.31   817.2 1610.54   842.2 1638.64   862.1 1651.97   887.1 1664.29
   936.4 1702.81   965.6 1731.82   999.8 1754.99  1014.4 1768.87  1024.2 1776.22
#Mann= 3 , 0 , 0
       0     0.1       0   449.6   0.045       0   466.7     0.1       0
Bank Sta=   449.6,   466.7
Exp/Cntr=0.3,0.1

Type RM Length L Ch R = 1 ,2547.6,253.6,256.8,258.6
XS GIS Cut Line= 2
     1798603.799      185795.677     1799158.854      185152.982
#Sta/Elev= 30
       0 1631.67    30.0 1607.40    59.9 1585.69    99.9 1558.64   124.9 1539.28
   234.8 1477.76   279.7 1455.08   314.7 1430.79   334.7 1418.75   344.7 1415.37
   359.7 1414.86   370.8 1411.68   379.6 1410.10   388.3 1410.99   424.6 1417.71
   454.6 1429.53   459.6 1431.94   479.6 1449.16   489.5 1455.66   514.5 1465.53
   539.5 1469.29   564.5 1482.09   584.4 1494.34   614.4 1506.06   634.4 1516.44
   649.4 1520.33   669.4 1523.26   704.3 1540.74   739.3 1550.98   849.2 1589.19
#Mann= 3 , 0 , 0
       0     0.1       0   370.8   0.045       0   388.3     0.1       0
Bank Sta=   370.8,   388.3
Exp/Cntr=0.3,0.1

Type RM Length L Ch R = 1 ,2290.8,502.8,503.6,505.8
XS GIS Cut Line= 3
     1798675.645      186007.016     1799018.127      185707.242
     1799343.956      185386.596
#Sta/Elev= 30
       0 1642.40    24.7 1629.74    54.4 1618.82    74.2 1607.84   118.7 1586.36
   183.0 1544.51   212.7 1526.73   267.2 1497.09   311.7 1467.83   336.4 1453.38
   356.2 1443.49   371.0 1432.95   390.8 1415.14   400.7 1407.75   431.5 1406.33
   440.3 1405.98     449 1406.16   460.1 1406.75   475.0 1411.27   539.6 1435.82
   594.3 1474.53   624.1 1488.68   653.9 1491.27   688.7 1503.97   698.6 1506.41
   768.2 1510.18   798.0 1516.03   807.9 1521.07   862.6 1556.72   912.3 1585.17
#Mann= 3 , 0 , 0
       0     0.1       0   431.5   0.045       0     449     0.1       0
Bank Sta=   431.5,     449
Exp/Cntr=0.3,0.1

Type RM Length L Ch R = 1 ,1787.2,494.7,500.8,506.9
XS GIS Cut Line= 3
     1798896.720      186379.295     1799191.314      186178.697
     1799654.142      185807.244
#Sta/Elev= 30
       0 1648.12    24.8 1636.81   118.8 1581.14   143.6 1561.83   163.4 1548.54
   183.2 1540.01   232.6 1511.49   257.4 1501.54   326.7 1457.50   381.3 1430.59
   426.2 1397.15   441.2 1391.25     452 1389.50   461.1 1389.04   470.1 1389.46
   506.0 1391.00   531.0 1397.39   550.9 1405.00   605.8 1449.32   615.7 1455.07
   630.7 1459.18   680.6 1497.60   710.5 1512.34   750.4 1513.67   765.3 1518.16
   780.3 1528.78   820.2 1568.65   845.1 1588.31   910.0 1625.96   949.9 1634.34
#Mann= 3 , 0 , 0
       0     0.1       0     452   0.045       0   470.1     0.1       0
Bank Sta=     452,   470.1
Exp/Cntr=0.3,0.1

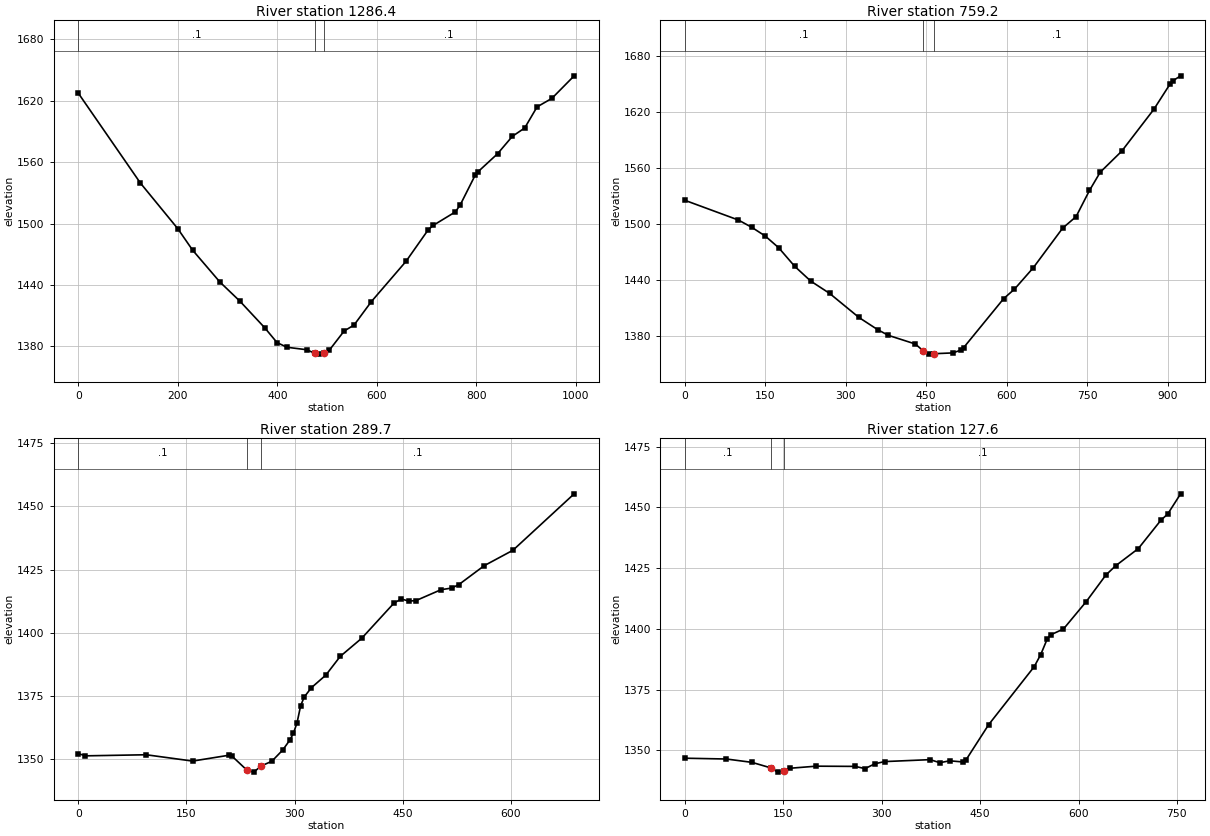
Type RM Length L Ch R = 1 ,1286.4,540.9,527.2,513.4
XS GIS Cut Line= 3
     1799159.997      186638.538     1799661.974      186428.634
     1799986.568      186113.778
#Sta/Elev= 30
       0 1627.42   124.8 1539.56   199.7 1495.10   229.6 1474.04   284.5 1442.85
   324.5 1424.24   374.4 1398.23   399.3 1383.66   419.3 1379.10   459.2 1376.68
   474.9 1373.22   484.2 1372.40   493.4 1373.60   504.2 1376.16   534.1 1395.01
   554.0 1400.82   588.8 1423.73   658.4 1463.06   703.1 1493.96   713.0 1498.22
   757.8 1511.46   767.7 1518.57   797.5 1547.36   802.5 1550.37   842.3 1568.21
   872.1 1585.27   896.9 1593.42   921.8 1614.05   951.6 1622.40   996.3 1644.41
#Mann= 3 , 0 , 0
       0     0.1       0   474.9   0.045       0   493.4     0.1       0
Bank Sta=   474.9,   493.4
Exp/Cntr=0.3,0.1

Type RM Length L Ch R = 1 ,759.2,473.8,469.6,465.4
XS GIS Cut Line= 3
     1799665.588      187183.484     1799967.092      186724.014
     1800188.720      186421.887
#Sta/Elev= 30
       0 1525.23    99.9 1504.06   124.9 1496.23   149.9 1486.93   174.9 1474.42
   204.8 1454.48   234.8 1438.59   269.8 1425.49   324.7 1399.59   359.7 1386.50
   379.7 1380.41   429.7 1371.19   444.9 1363.63   454.6 1360.33   464.2 1360.77
   499.6 1361.63   514.6 1364.62   519.6 1367.14   594.5 1419.86   614.5 1429.93
   649.5 1452.82   704.4 1495.39   729.4 1507.70   754.4 1535.76   774.4 1555.31
   814.4 1577.79   874.3 1622.66   904.3 1649.54   909.3 1653.09   924.3 1658.62
#Mann= 3 , 0 , 0
       0     0.1       0   444.9   0.045       0   464.2     0.1       0
Bank Sta=   444.9,   464.2
Exp/Cntr=0.3,0.1

Type RM Length L Ch R = 1 ,289.7,153.9,162.1,170.3
XS GIS Cut Line= 3
     1800108.808      187183.904     1800258.010      187147.642
     1800463.544      186654.773
#Sta/Elev= 30
       0 1352.28     9.9 1351.39    94.1 1351.82   158.5 1349.32   208.4 1351.61
   213.4 1351.19   233.5 1345.81   243.4 1344.95   253.2 1347.35   268.3 1349.24
   283.3 1353.65   293.3 1357.61   298.3 1360.32   303.3 1364.48   308.3 1371.21
   313.2 1374.63   323.2 1378.34   343.2 1383.31   363.2 1390.72   393.1 1397.92
   438.0 1411.88   448.0 1413.42   458.0 1412.60   468.0 1412.76   502.9 1417.09
   517.9 1417.75   527.8 1419.14   562.8 1426.58   602.7 1432.69   687.6 1455.01
#Mann= 3 , 0 , 0
       0     0.1       0   233.5   0.045       0   253.2     0.1       0
Bank Sta=   233.5,   253.2
Exp/Cntr=0.3,0.1

Type RM Length L Ch R = 1 ,127.6,132.5,127.6,122.6
XS GIS Cut Line= 3
     1800318.580      187277.059     1800442.611      187145.996
     1800541.609      186579.425
#Sta/Elev= 30
       0 1346.75    63.4 1346.42   102.4 1345.04   131.4 1342.74   141.4 1341.02
   151.3 1341.68   160.9 1342.63   200.3 1343.47   259.8 1343.38   274.6 1342.46
   289.5 1344.44   304.4 1345.36   373.8 1346.16   388.7 1344.90   403.6 1345.68
   423.4 1345.22   428.4 1345.99   463.1 1360.58   532.5 1384.45   542.4 1389.42
   552.3 1395.83   557.3 1397.51   577.1 1399.96   611.8 1411.24   641.6 1422.14
   656.4 1425.94   691.1 1433.05   725.8 1444.82   735.8 1447.24   755.6 1455.60
#Mann= 3 , 0 , 0
       0     0.1       0   131.4   0.045       0   151.3     0.1       0
Bank Sta=   131.4,   151.3
Exp/Cntr=0.3,0.1